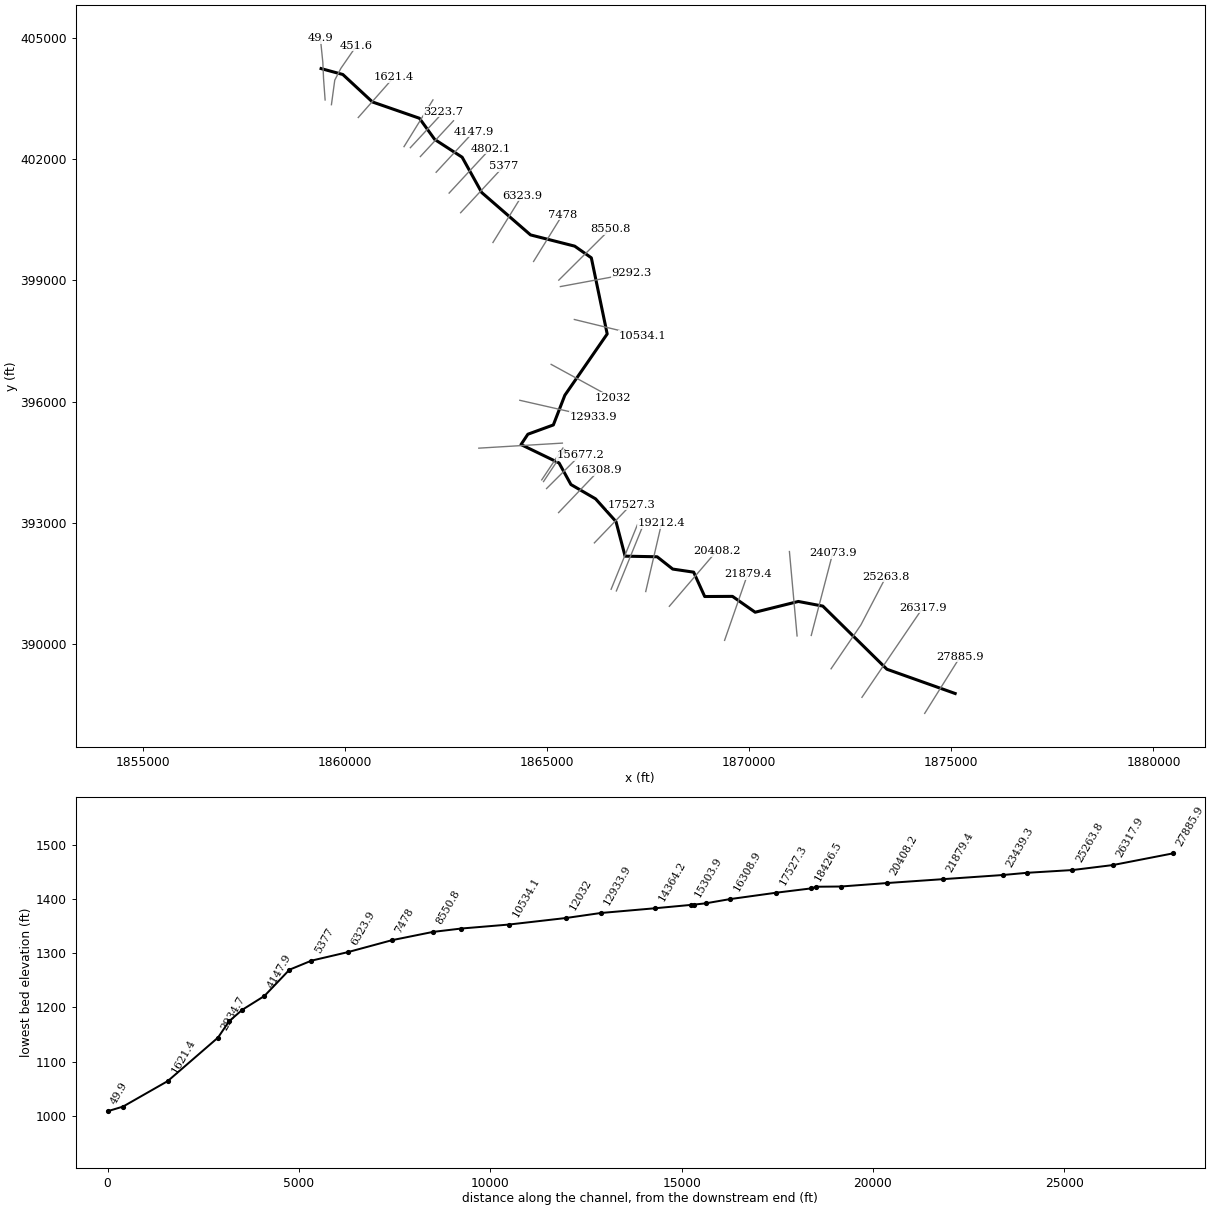
--- DeckersCk.prj (project) ---

Proj Title=DeckersCk
Current Plan=p01
Default Exp/Contr=0,0
English Units
Geom File=g01
Flow File=f01
Plan File=p01
BEGIN DESCRIPTION:
At d/s limits, the model ties into a AE (detailed) study; the Know WSEL of 1016.5ft is obtained from the FIS profile chart (07P).
END DESCRIPTION:
DSS Export Rating Curves= 0
DSS Export Rating Curve Sorted= 0
DSS Export Volume Flow Curves= 0
DXF OffsetX= 0
DXF OffsetY= 0
DXF ScaleX= 0
DXF ScaleY= 0

--- DeckersCk.p01 (plan) ---

Plan Title=Floodplain
Program Version=4.00
Geom File=g01
Flow File=f01
K Sum by GR=0
Std Step Tol=0.01
Critical Tol=0.01
Num of Std Step Trials=20
Max Error Tol=0.3
Flow Tol Ratio=0.001
Split Flow NTrial=30
Split Flow Tol=0.02
Split Flow Ratio=0.02
Log Output Level=0
Friction Slope Method=1
Unsteady Friction Slope Method=2
Unsteady Bridges Friction Slope Method=1
Global Log Level=0
CheckData=False
Run HTab=0
Run UNet=0
Run PostProcess=0
UNET Theta=0
UNET Theta Warmup=0
UNET ZTol=0
UNET ZSATol=0
UNET MxIter=0
UNET MaxInSteps=0
UNET DtIC=0
UNET DtMin=0
UNET MaxCRTS=0
UNET WFStab=0
UNET SFStab=0
UNET WFX=0
UNET SFX=0
UNET DSS MLevel=0
UNET DZMax Abort=0
UNET Convert EG Bridges=0
UNET Use Existing IB Tables=0
UNET Froude Limit=0
UNET Froude Power=0
Write IC File=0
Echo Input=False
Echo Output=False
Write Detailed=0

--- DeckersCk.f01 (steady flow) ---

Flow Title=NFF Regression Equation
Program Version=4.10
Number of Profiles= 1
Profile Names=P100yr
River Rch & RM=DeckersCk,Main            ,27885.9
    5818
River Rch & RM=DeckersCk,Main            ,19212.4
    6306
River Rch & RM=DeckersCk,Main            ,12933.9
    6498
River Rch & RM=DeckersCk,Main            ,451.6
    6820
River Rch & RM=DeckersCk,Main            ,49.9
    7411
Boundary for River Rch & Prof#=DeckersCk,Main            , 1
Up Type= 0
Dn Type= 1
Dn Known WS=1016.5
DSS Import GetInterval= 0
DSS Import GetPeak= 0
DSS Import FillOption= 0

--- DeckersCk.g01 (geometry) ---

Geom Title=USGS 10m DEM
Program Version=4.10

River Reach=DeckersCk       ,Main
Reach XY= 30
     1875094.279      388786.861     1873405.782      389386.622
     1871819.659      390947.667      1871214.58      391062.486
     1870145.668      390796.397      1869584.33       391188.24
     1868897.237      391184.595     1868623.858      391786.758
     1868105.896      391863.304      1867719.52      392167.666
     1866926.903      392182.246     1866702.368      393037.011
     1866196.799      393599.808     1865586.981      393953.378
     1865293.554      394486.285     1864352.037      394941.552
     1864521.532       395197.07     1865152.126      395426.709
     1865436.258      396160.093     1866484.208      397676.029
     1866091.983      399558.832     1865680.553      399847.308
     1864587.066      400125.302     1863379.588      401173.432
     1862895.293      402046.253     1862217.201       402485.19
     1861838.213      403009.446     1860675.662       403412.28
     1859943.501      404091.085     1859405.361      404237.657

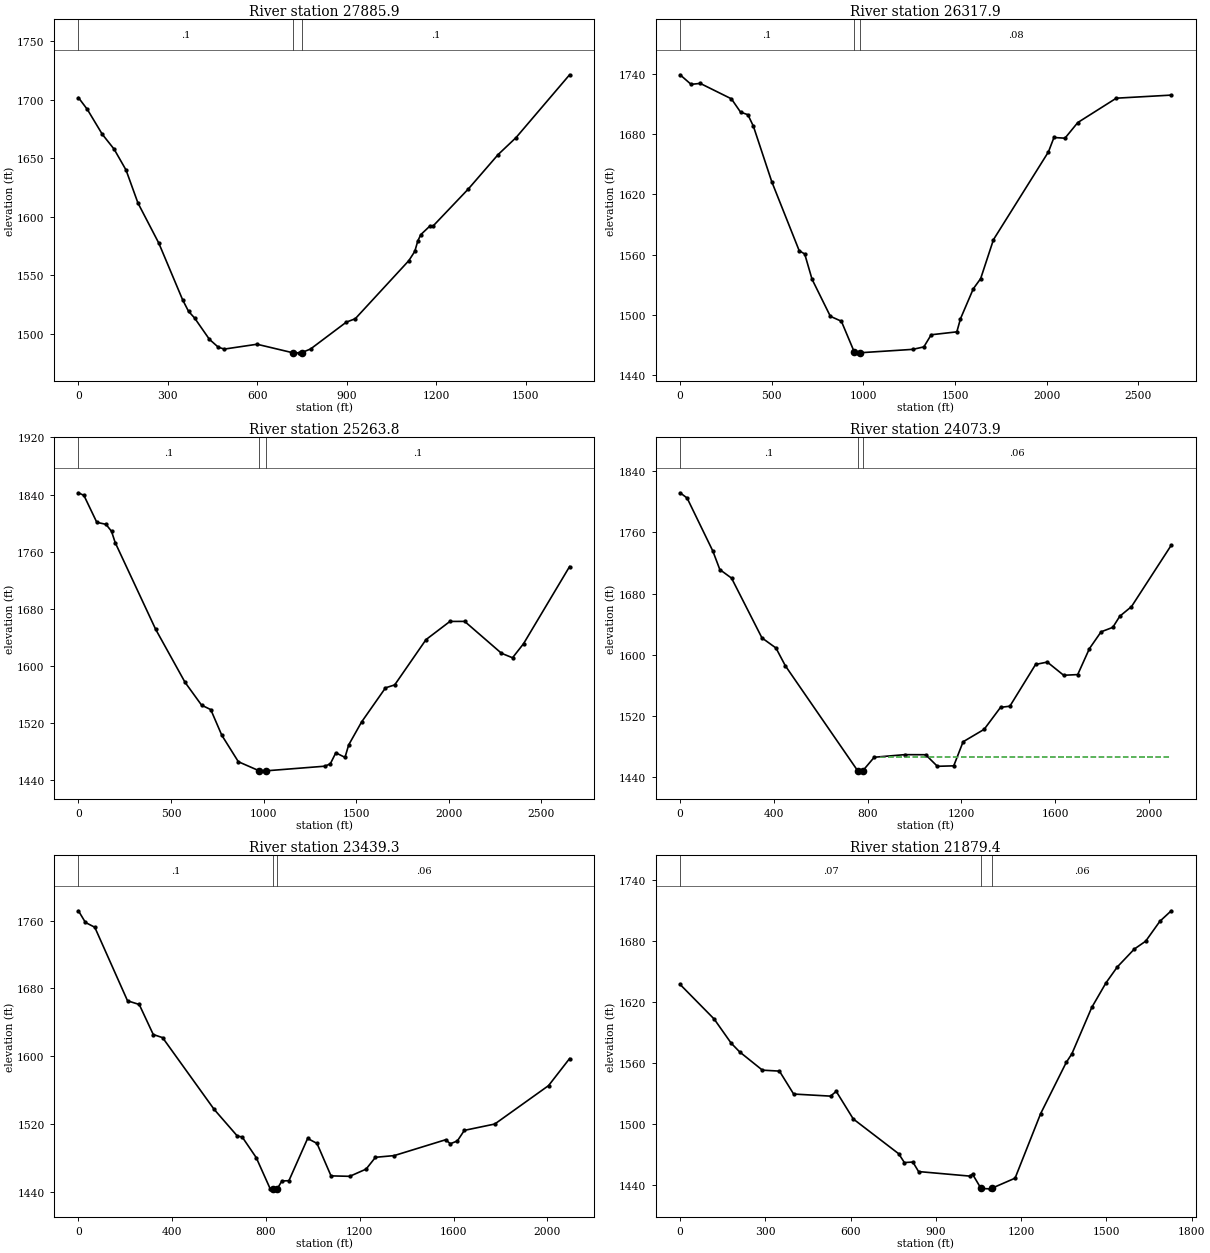
Type RM Length L Ch R = 1 ,27885.9 ,1568.7,1568,1566.5
XS GIS Cut Line= 2
     1874340.685      388295.458     1875215.685      389691.292
#Sta/Elev= 30
       0 1701.75      30 1691.65    79.9  1670.5   119.8 1657.72   159.8 1639.86
   199.7 1611.72   269.6 1577.48   349.4 1529.15   369.4 1519.23   389.4 1513.62
   439.3 1495.34   469.3 1488.58   489.2 1486.99   599.1 1491.13  718.171483.908
   738.8 1483.79   748.8 1483.93   778.8 1487.11   898.6 1510.02   928.5  1512.9
  1108.3 1562.56  1128.2 1570.43  1138.2 1579.26  1148.2  1584.7  1178.2 1591.92
  1188.1 1591.72    1308 1623.78  1407.8 1653.14  1467.7 1667.58  1647.4 1721.25
#Mann= 3 , 0 , 0
       0      .1       0  718.17    .045       0   748.8      .1       0
#XS Ineff= 2 , 0
           599.1 1491.13
Permanent Ineff=
       F       F
Bank Sta=718.17,748.8
XS Rating Curve= 0 ,0
Exp/Cntr=0.3,0.1

Type RM Length L Ch R = 1 ,26317.9 ,1053,1054.1,1055.2
XS GIS Cut Line= 2
     1872788.147      388692.679     1874295.063      390907.368
#Sta/Elev= 30
       0 1738.93      60  1729.4     110 1730.35   279.9    1715   329.8 1701.78
   369.8  1699.2   399.8 1687.77   499.8 1632.65   649.7 1563.89   679.7 1560.65
   719.7 1535.52   819.6 1498.63   879.6 1493.76   949.6 1463.32   969.5  1462.3
  980.341462.369  1269.4 1465.77  1329.4  1468.2  1369.4 1480.28  1509.3 1483.18
  1529.3 1496.26  1599.2 1526.06  1639.2 1536.12  1709.2 1574.94    2009 1662.26
    2039 1676.54    2099 1675.84    2169 1691.42  2378.9 1715.64  2678.7 1718.71
#Mann= 3 , 0 , 0
       0      .1       0   949.6    .045       0  980.34     .08       0
Bank Sta=949.6,980.34
XS Rating Curve= 0 ,0
Exp/Cntr=0.3,0.1

Type RM Length L Ch R = 1 ,25263.8 ,1183.7,1189.9,1196
XS GIS Cut Line= 3
     1872023.845      389397.889     1872761.358      390481.799
     1873382.352      391672.195
#Sta/Elev= 30
       0 1842.42    29.8 1838.71    99.3 1801.07     149 1798.24   178.8 1788.52
   198.6 1772.72   417.1 1651.39   576.1 1577.05   665.4 1545.12   715.1 1538.84
   774.7 1502.95   864.1  1465.9   973.3 1453.57  1013.1 1453.14 1013.781453.164
  1330.9 1459.63  1360.8 1462.89  1390.6 1478.36  1440.3 1471.98  1460.2 1489.46
  1529.8  1521.5  1659.1 1569.34  1708.8 1573.45  1877.9 1636.83  2007.2 1662.31
  2086.8 1662.36  2285.7 1617.72  2345.4 1611.45    2405 1631.15  2653.7 1739.15
#Mann= 3 , 0 , 0
       0      .1       0   973.3    .045       0 1013.78      .1       0
Bank Sta=973.3,1013.78
XS Rating Curve= 0 ,0
Exp/Cntr=0.3,0.1

Type RM Length L Ch R = 1 ,24073.9 ,626.8,634.7,642.5
XS GIS Cut Line= 2
     1871533.393      390222.542     1872062.907      392249.451
#Sta/Elev= 30
       0 1811.91    29.9 1805.06   139.7 1735.65   169.6 1711.37   219.5 1700.24
   349.2    1622     409 1608.76   448.9 1585.55   757.5 1448.15   758.2 1448.04
  779.171448.086     828 1465.81   957.7 1469.22  1047.5 1469.12  1097.4 1453.97
  1167.2 1454.58  1207.1 1486.07  1296.9 1502.36  1366.7 1531.08  1406.6 1532.64
  1516.3 1587.27  1566.2 1590.37    1636  1573.1  1695.9 1573.99  1745.8 1607.95
  1795.7 1629.98  1845.5 1635.78  1875.5 1650.41  1925.3 1662.94  2094.9 1743.28
#Mann= 3 , 0 , 0
       0      .1       0   757.5    .045       0  779.17     .06       0
#XS Ineff= 2 , 0
                          852.59         1466.74
Permanent Ineff=
       F       F
Bank Sta=757.5,779.17
XS Rating Curve= 0 ,0
Exp/Cntr=0.3,0.1

Type RM Length L Ch R = 1 ,23439.3 ,1569.5,1559.9,1550.2
XS GIS Cut Line= 2
     1871182.738      390210.176     1870993.424      392296.539
#Sta/Elev= 30
       0 1771.46    29.9 1757.72    69.8 1752.05   209.5 1665.43   259.4  1661.1
   319.2 1625.73   359.1 1622.02   578.6 1537.65   678.4 1505.96   698.3 1505.14
   758.2 1480.82     818 1443.99     828 1443.96     848 1444.01   867.9 1453.21
   897.8 1453.55   977.6 1503.28  1017.5 1497.49  1077.4 1459.23  1157.2  1458.7
    1227  1467.2  1266.9  1481.1  1346.7 1483.11  1566.2 1501.78  1586.2 1497.08
  1616.1 1500.33    1646 1512.82  1775.7 1520.28  2005.2 1565.55  2094.9 1597.41
#Mann= 3 , 0 , 0
       0      .1       0     828    .045       0     848     .06       0
Bank Sta=828,848
XS Rating Curve= 0 ,0
Exp/Cntr=0.3,0.1

Type RM Length L Ch R = 1 ,21879.4 ,1480,1471.2,1462.3
XS GIS Cut Line= 2
     1869389.296      390101.014     1869957.873      391732.958
#Sta/Elev= 30
       0 1637.01   119.9 1603.04   179.8 1579.33   209.8 1570.72   289.7 1552.84
   349.6 1551.91   399.6  1529.4   529.4 1527.35   549.4 1532.04   609.4 1504.92
   769.2 1470.78   789.2 1462.15   819.1 1462.64   839.1  1453.3  1018.9 1448.86
  1028.9 1450.77  1058.9 1436.69  1088.8 1436.34  1098.8 1437.14  1178.7 1446.82
  1268.6 1510.14  1358.6 1560.37  1378.5 1568.87  1448.4 1614.36  1498.4 1638.49
  1538.4 1654.18  1598.3 1671.74  1638.2 1679.45  1688.2    1699  1728.2  1709.3
#Mann= 3 , 0 , 0
       0     .07       0  1058.9    .045       0  1098.8     .06       0
Bank Sta=1058.9,1098.8
XS Rating Curve= 0 ,0
Exp/Cntr=0.3,0.1

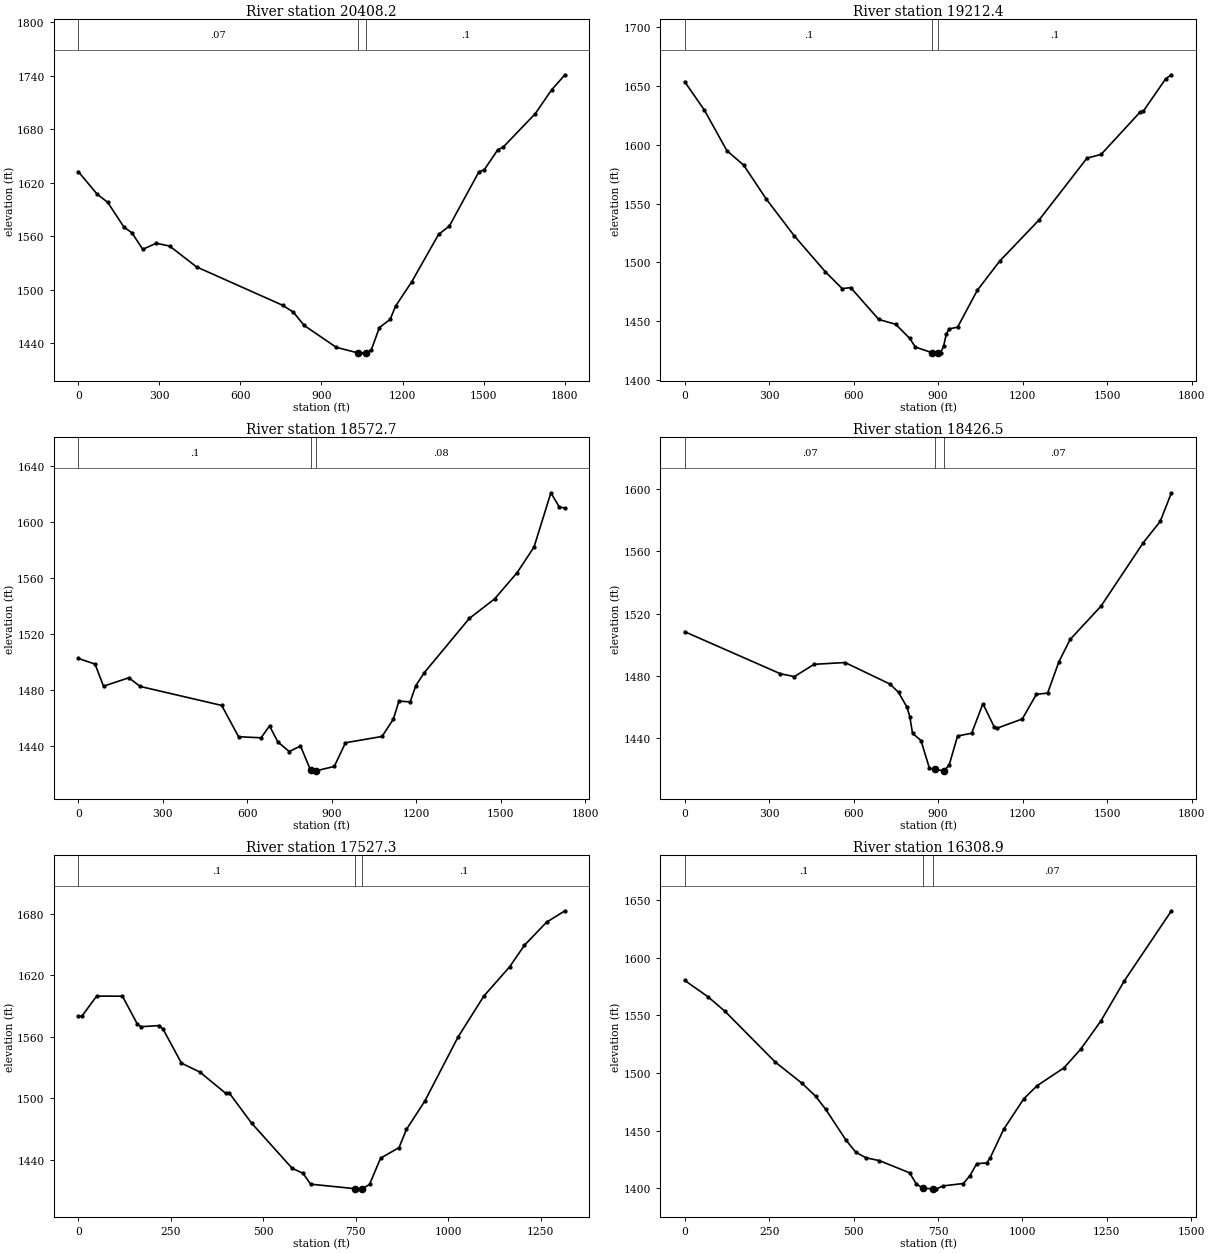
Type RM Length L Ch R = 1 ,20408.2 ,1184.9,1195.8,1206.7
XS GIS Cut Line= 2
     1868022.109      390943.028     1869193.984      392310.215
#Sta/Elev= 30
       0 1632.53    69.6 1607.28   109.4 1597.87   169.1 1570.24     199 1563.68
   238.8 1545.26   288.5 1552.02   338.2 1548.93   437.7 1525.55   756.1 1482.52
   795.9 1474.79   835.7 1459.92   955.1 1435.26 1033.691429.181  1043.9 1429.15
 1065.331429.172  1084.4 1432.54  1114.2 1457.47    1154 1466.68  1173.9 1481.44
  1233.6  1508.7  1333.1 1561.97  1372.9 1571.29  1482.3 1632.11  1502.2 1634.49
    1552 1656.86  1571.9  1659.8  1691.3 1697.57    1751 1724.01  1800.7 1741.01
#Mann= 3 , 0 , 0
       0     .07       0 1033.69    .045       0 1065.33      .1       0
Bank Sta=1033.69,1065.33
XS Rating Curve= 0 ,0
Exp/Cntr=0.3,0.1

Type RM Length L Ch R = 1 ,19212.4 ,643.4,639.7,636.1
XS GIS Cut Line= 2
     1867438.031      391307.983     1867829.277      392991.268
#Sta/Elev= 30
       0 1653.79    69.9 1629.61   149.8 1595.07   209.8 1582.59   289.7 1553.81
   389.6 1522.32   499.5 1491.84   559.4 1477.47   589.4 1478.36   689.3 1451.21
   749.2 1447.13   799.2 1435.04   819.1 1427.73  878.831422.868     889 1422.79
     899 1422.79     909  1422.8     919 1428.26     929 1438.84     939 1443.16
     969 1444.66  1038.9 1476.03  1118.8 1501.03  1258.7  1536.1  1428.5 1588.68
  1478.4 1591.79  1618.3 1628.22  1628.3 1628.66  1708.2 1656.37  1728.2 1659.66
#Mann= 3 , 0 , 0
       0      .1       0  878.83    .045       0     899      .1       0
Bank Sta=878.83,899
XS Rating Curve= 0 ,0
Exp/Cntr=0.3,0.1

Type RM Length L Ch R = 1 ,18572.7 ,144.2,146.1,148.1
XS GIS Cut Line= 2
     1866711.392      391322.874     1867363.653      392923.211
#Sta/Elev= 30
       0 1502.63    59.9 1498.56    89.9 1482.77   179.8  1488.8   219.8 1482.62
   509.5 1469.06   569.4 1446.73   649.3 1445.96   679.3 1454.42   709.2 1442.92
   749.2 1436.16   789.2 1440.11   825.1  1422.8   829.1 1422.38  844.67 1422.42
     909 1425.49     949 1442.42  1078.8 1446.91  1118.8 1459.26  1138.8 1472.13
  1178.7  1471.6  1198.7  1483.2  1228.7 1492.41  1388.5 1531.12  1478.4 1545.08
  1558.3  1563.8  1618.3 1582.06  1678.2 1620.82  1708.2  1610.6  1728.2 1609.99
#Mann= 3 , 0 , 0
       0      .1       0   825.1    .045       0  844.67     .08       0
Bank Sta=825.1,844.67
XS Rating Curve= 0 ,0
Exp/Cntr=0.3,0.1

Type RM Length L Ch R = 1 ,18426.5 ,909.6,899.2,888.8
XS GIS Cut Line= 2
     1866581.606      391363.886     1867233.867      392964.223
#Sta/Elev= 30
       0 1508.47   339.6 1481.52   389.6 1479.68   459.5 1487.55   569.4  1488.7
   729.2 1474.87   759.2 1469.55   789.2 1460.11   799.2 1454.08   809.1 1443.27
   839.1 1438.69   869.1 1420.85   888.3  1420.2     919 1419.25  920.511419.381
     939 1422.94     969  1441.6  1018.9 1443.36  1058.9 1462.27  1098.8 1447.52
  1108.8 1446.57  1198.7 1452.51  1248.7 1468.34  1288.6 1469.09  1328.6 1489.16
  1368.5 1503.49  1478.4  1524.9  1628.3 1565.57  1688.2 1579.14  1728.2 1597.54
#Mann= 3 , 0 , 0
       0     .07       0   888.3    .045       0  920.51     .07       0
Bank Sta=888.3,920.51
XS Rating Curve= 0 ,0
Exp/Cntr=0.3,0.1

Type RM Length L Ch R = 1 ,17527.3 ,1218.2,1218.4,1218.6
XS GIS Cut Line= 2
     1866167.074      392510.736     1867078.532      393459.087
#Sta/Elev= 30
       0 1579.69      10 1579.88    49.8 1599.47   119.6 1599.42   159.4 1572.46
   169.4 1569.61   219.2 1570.74   229.2 1567.34     279 1534.09   328.8 1525.35
   398.6 1504.64   408.6 1504.76   468.3 1475.65     578 1431.52   607.8 1426.55
   627.8    1416   747.4 1411.62   767.3 1411.44  767.751411.495   787.2 1415.78
   817.1 1441.38   866.9 1451.66   886.9 1469.36   936.7 1497.12  1026.4 1559.58
  1096.1 1599.48  1165.9  1628.1  1205.7 1649.05  1265.5 1671.55  1315.3 1682.72
#Mann= 3 , 0 , 0
       0      .1       0   747.4    .045       0  767.75      .1       0
Bank Sta=747.4,767.75
XS Rating Curve= 0 ,0
Exp/Cntr=0.3,0.1

Type RM Length L Ch R = 1 ,16308.9 ,630.4,631.7,633.1
XS GIS Cut Line= 2
     1865281.657      393259.434     1866277.751      394301.101
#Sta/Elev= 30
       0 1580.27    69.6 1565.95   119.3 1553.49   268.4 1509.41   347.9 1490.96
   387.6 1479.86   417.5 1468.56   477.1 1441.99   506.9 1431.23   536.8 1426.46
   576.5 1424.01     666 1413.43   685.8 1403.87   705.7    1400   735.6 1399.59
   745.5 1399.54   765.4  1402.1     825 1404.16   844.9 1411.02   864.8 1421.39
   894.6 1421.98   904.5 1426.31   944.3 1450.99  1003.9 1477.56  1043.7 1488.99
  1123.2 1504.46  1172.9 1520.71  1232.5 1545.15  1302.1 1579.98  1441.3 1640.62
#Mann= 3 , 0 , 0
       0      .1       0   705.7    .045       0   735.6     .07       0
Bank Sta=705.7,735.6
XS Rating Curve= 0 ,0
Exp/Cntr=0.3,0.1

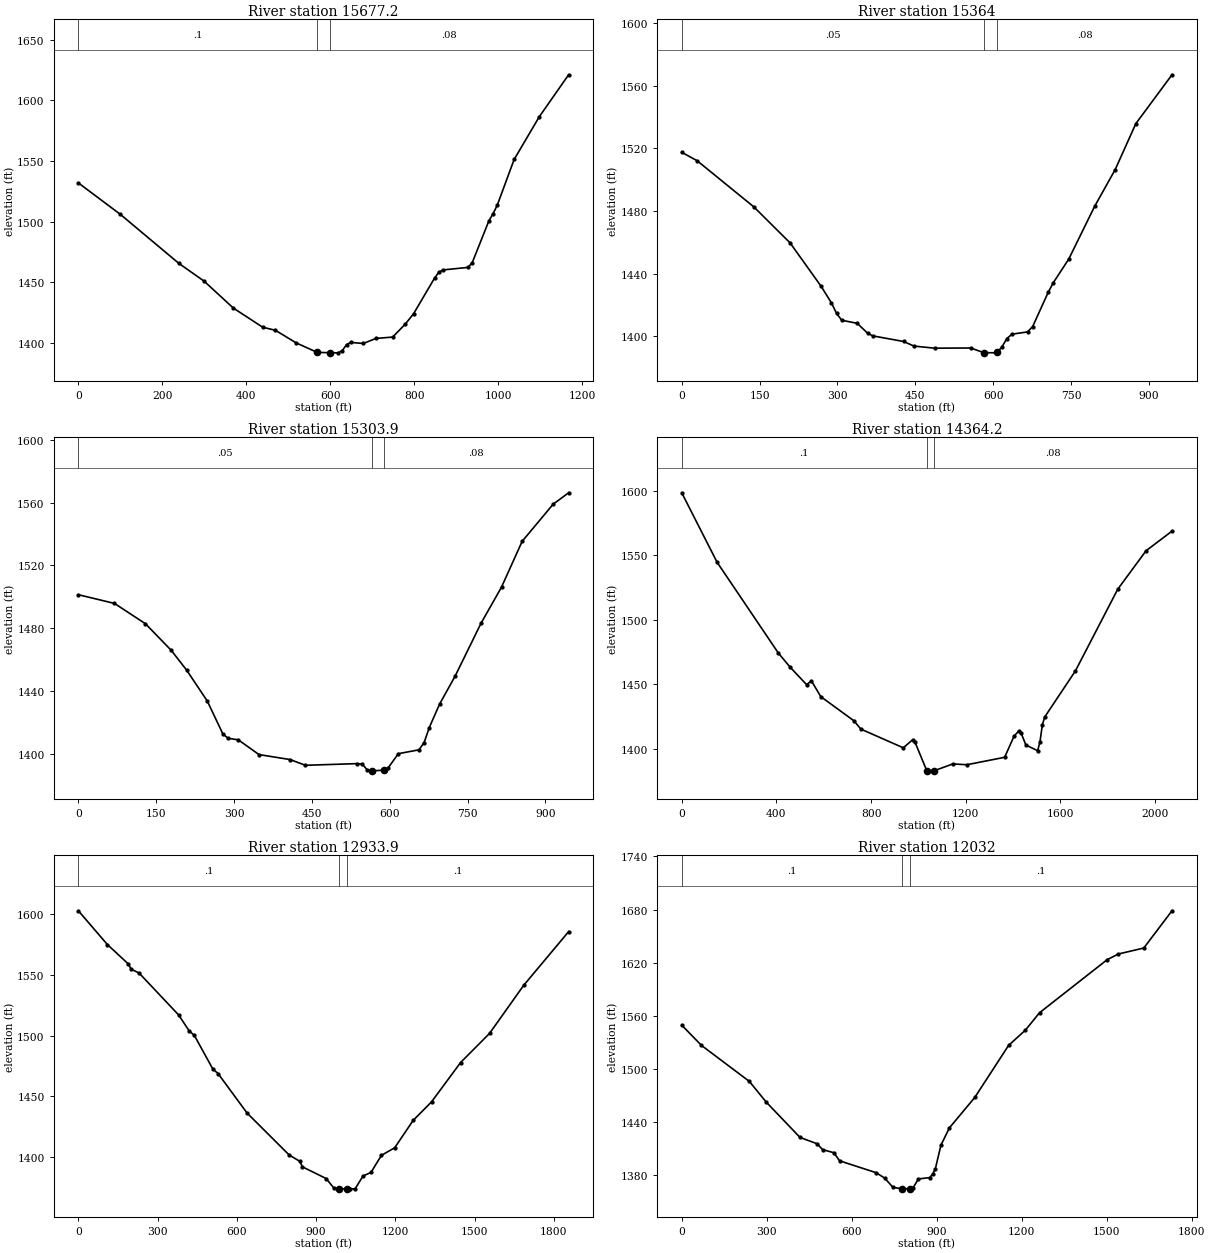
Type RM Length L Ch R = 1 ,15677.2 ,310.3,313.2,316
XS GIS Cut Line= 2
     1864984.348      393854.052     1865811.171      394678.705
#Sta/Elev= 30
       0 1531.81    99.8 1505.96   239.5 1465.48   299.4 1450.89   369.3 1428.65
   439.2 1412.86   469.1 1410.42     519 1399.95   568.9 1392.18   598.9 1391.89
   618.8 1391.79   628.8 1393.68   638.8 1398.58   648.8 1400.39   678.7  1399.5
   708.6 1403.64   748.6 1404.79   778.5 1415.37   798.5 1424.03   848.4 1453.33
   858.4 1458.13   868.3 1460.11   928.2 1462.19   938.2 1466.08   978.1 1500.77
   988.1 1506.53   998.1 1513.74    1038 1551.12  1097.9 1586.34  1167.8 1620.93
#Mann= 3 , 0 , 0
       0      .1       0   568.9    .045       0   598.9     .08       0
Bank Sta=568.9,598.9
XS Rating Curve= 0 ,0
Exp/Cntr=0.3,0.1

Type RM Length L Ch R = 1 ,15364   ,60.2,60.2,60.2
XS GIS Cut Line= 2
     1864909.261      394027.229     1865432.699      394813.688
#Sta/Elev= 30
       0 1517.41    29.8 1511.99   139.2 1482.48   208.8 1459.56   268.5 1431.89
   288.4 1421.31   298.3 1414.58   308.3 1410.18   338.1 1408.24     358 1401.98
     368 1400.22   427.6 1396.62   447.5 1393.69   487.3 1392.36   556.9 1392.47
   581.8 1389.51   606.6 1389.38  607.531389.709   616.6 1392.92   626.5 1398.49
   636.4  1401.3   666.3 1402.74   676.2 1406.16   706.1 1427.96     716 1434.16
   745.8 1449.25   795.6 1482.87   835.3  1506.4   875.1 1535.74   944.7 1566.89
#Mann= 3 , 0 , 0
       0     .05       0   581.8    .045       0  607.53     .08       0
Bank Sta=581.8,607.53
XS Rating Curve= 0 ,0
Exp/Cntr=0.3,0.1

Type RM Length L Ch R = 1 ,15303.9 ,961,939.6,918.3
XS GIS Cut Line= 2
     1864864.991      394068.896     1865388.428      394855.354
#Sta/Elev= 30
       0 1501.25    69.6 1495.69   129.3 1482.74     179 1465.77   208.8  1453.1
   248.6 1433.38   278.4 1412.53   288.4 1409.76   308.3 1408.73   348.1 1399.34
   407.7  1396.2   437.6 1392.53     537 1393.59     547 1393.27   556.9 1389.53
   566.4 1389.01   566.8 1388.99  588.481389.422   596.7 1390.77   616.6 1399.93
   656.3 1402.38   666.3 1407.04   676.2 1416.58   696.1 1431.55     726 1449.36
   775.7 1482.92   815.4  1506.1   855.2 1535.28   914.9 1558.93   944.7 1566.21
#Mann= 3 , 0 , 0
       0     .05       0   566.4    .045       0  588.48     .08       0
Bank Sta=566.4,588.48
XS Rating Curve= 0 ,0
Exp/Cntr=0.3,0.1

Type RM Length L Ch R = 1 ,14364.2 ,1436.9,1430.3,1423.7
XS GIS Cut Line= 2
     1863307.699       394852.75     1865375.407       394977.75
#Sta/Elev= 30
       0 1598.63   149.4 1544.68   408.3  1474.2   458.1 1463.23   527.8 1449.65
   547.8  1452.7   587.6 1440.38     727 1421.72   756.9 1415.19   936.2 1400.67
     976 1406.98     986 1404.91 1035.45 1382.85  1035.7 1382.79  1065.6 1382.79
  1145.3 1388.15    1205 1387.53  1364.4 1393.31  1404.2 1409.71  1424.1 1413.72
  1434.1  1412.1    1454 1402.85  1503.8  1398.4  1513.8 1405.47  1523.7 1418.43
  1533.7  1424.6  1663.2 1460.29  1842.4 1523.81  1961.9 1553.61  2071.5 1568.86
#Mann= 3 , 0 , 0
       0      .1       0 1035.45    .045       0  1065.6     .08       0
Bank Sta=1035.45,1065.6
XS Rating Curve= 0 ,0
Exp/Cntr=0.3,0.1

Type RM Length L Ch R = 1 ,12933.9 ,907.4,901.9,896.3
XS GIS Cut Line= 2
     1864322.456      396036.141     1866131.831      395624.625
#Sta/Elev= 30
       0  1602.8   109.7 1575.04   189.6 1558.93   199.5 1554.68   229.4 1551.66
   379.1 1517.17     419 1504.09     439 1500.23   508.8 1472.61   528.7 1468.85
   638.5 1436.36   798.1 1401.78     838 1396.64     848 1392.07   937.8 1382.46
   967.7 1374.44   987.6 1373.98  1017.6 1373.98  1027.6 1373.97  1047.5 1373.97
  1077.4 1384.58  1107.4 1387.42  1147.3 1401.57  1197.2 1407.76    1267 1430.22
  1336.8 1445.56  1446.6 1477.88  1556.3 1501.88    1686 1541.58  1855.6 1585.61
#Mann= 3 , 0 , 0
       0      .1       0   987.6    .045       0  1017.6      .1       0
Bank Sta=987.6,1017.6
XS Rating Curve= 0 ,0
Exp/Cntr=0.3,0.1

Type RM Length L Ch R = 1 ,12032   ,1492.7,1497.9,1503.1
XS GIS Cut Line= 2
     1865097.847      396924.162     1866616.944      396095.169
#Sta/Elev= 30
       0  1549.6    69.6 1526.74   238.7  1486.1   298.4 1462.67   417.7  1422.8
   477.4 1415.76   497.3 1409.08   537.1 1405.57     557 1396.48   686.3 1383.02
   716.1    1377   745.9 1366.41   775.8 1365.06   805.6 1364.81  806.511364.867
   815.6 1365.44   835.4 1375.97   875.2 1377.51   885.2 1381.22   895.1 1387.26
     915 1414.13   944.8 1433.62  1034.4 1467.98  1153.7  1526.7  1213.4 1544.07
  1263.1 1563.63  1501.8 1623.51  1541.6 1629.95  1631.1 1636.68  1730.6 1678.72
#Mann= 3 , 0 , 0
       0      .1       0   775.8    .045       0  806.51      .1       0
Bank Sta=775.8,806.51
XS Rating Curve= 0 ,0
Exp/Cntr=0.3,0.1

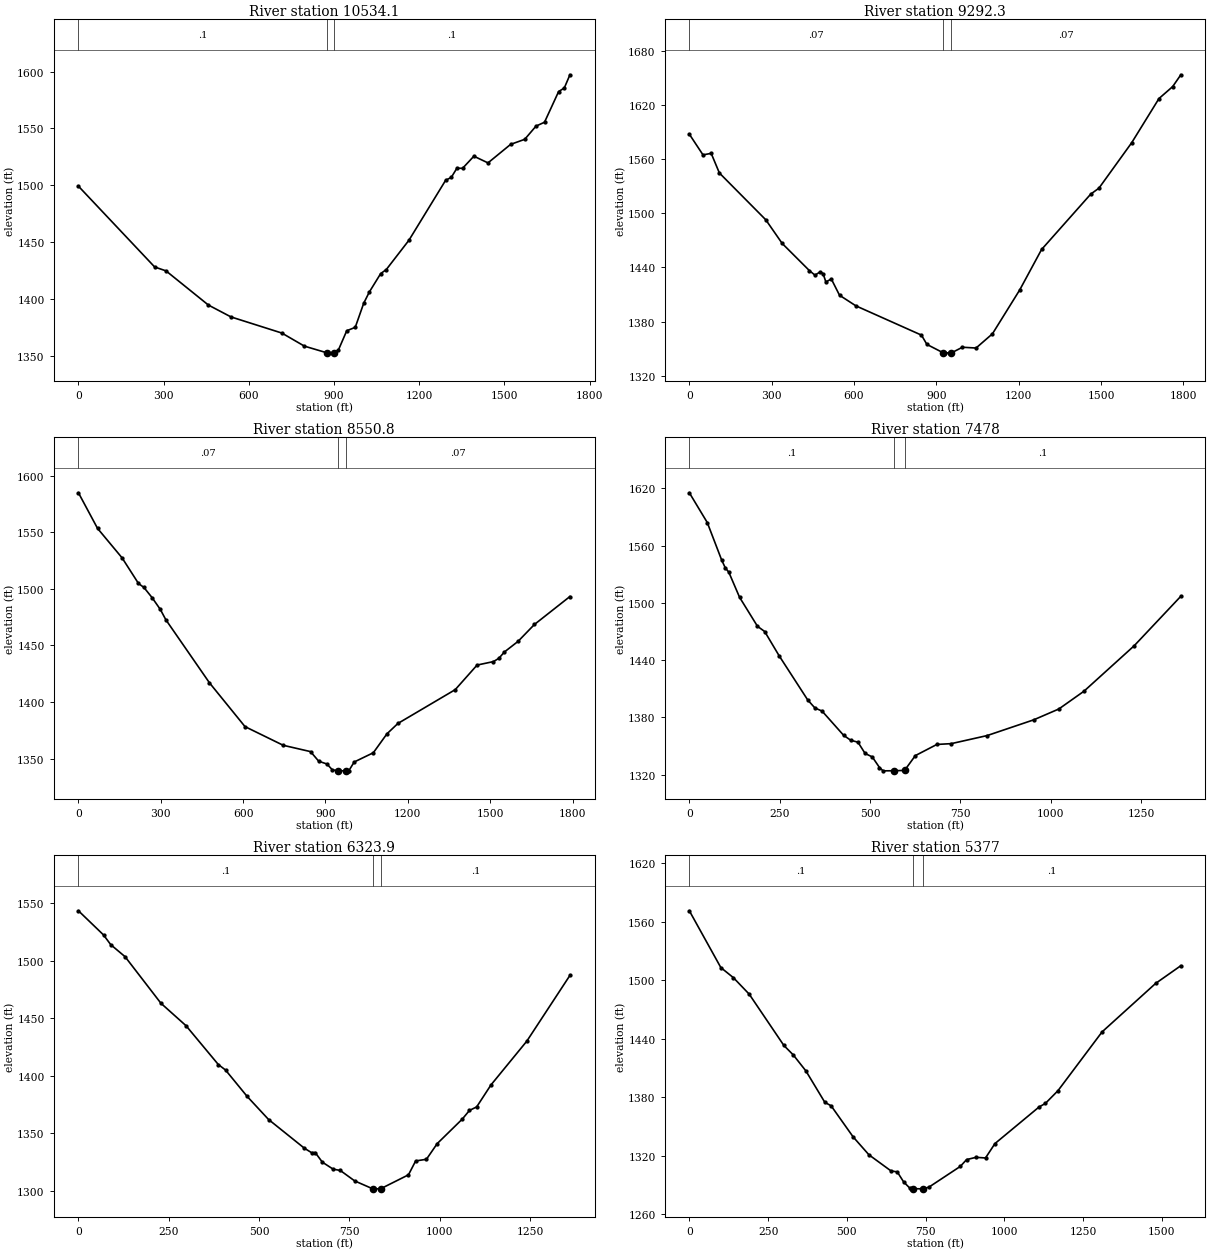
Type RM Length L Ch R = 1 ,10534.1 ,1232.2,1241.8,1251.4
XS GIS Cut Line= 2
     1865672.087      398033.956     1867353.467      397624.264
#Sta/Elev= 30
       0 1499.21   268.5 1428.16   308.3 1424.77   457.5 1394.73   537.1 1384.28
   716.1 1370.11   795.7 1358.59   875.2  1352.7   898.2 1352.81     915 1354.98
   944.8 1372.14   974.7 1375.12  1004.5 1396.31  1024.4 1406.23  1064.2 1422.34
  1084.1 1425.95  1163.7 1451.66    1293 1504.41  1312.8 1506.94  1332.7 1515.01
  1352.6 1514.92  1392.4 1525.56  1442.1 1519.68  1521.7 1535.94  1571.4  1540.4
  1611.2 1552.02  1641.1 1555.42  1690.8  1582.4  1710.7 1585.49  1730.6 1597.14
#Mann= 3 , 0 , 0
       0      .1       0   875.2    .045       0   898.2      .1       0
Bank Sta=875.2,898.2
XS Rating Curve= 0 ,0
Exp/Cntr=0.3,0.1

Type RM Length L Ch R = 1 ,9292.3  ,727.9,741.5,755.1
XS GIS Cut Line= 2
     1865326.145      398847.773     1867086.562      399174.162
#Sta/Elev= 30
       0  1587.6    49.7 1564.69    79.6 1566.35   109.4 1544.64   278.5 1492.75
   338.2 1466.57   437.7 1436.37   457.6 1431.46   477.4  1435.2   487.4 1432.98
   497.3 1423.91   517.2 1427.19   547.1 1409.18   606.8 1397.42   845.5 1365.01
   865.4 1354.71     925 1345.39   930.8 1345.38   954.9 1345.38   994.7 1351.58
  1044.4 1350.71  1104.1 1366.45  1203.6 1415.13  1283.1 1459.87  1462.2 1521.23
    1492 1527.78  1611.4 1578.16  1710.8  1627.1  1760.6 1640.31  1790.4 1653.41
#Mann= 3 , 0 , 0
       0     .07       0     925    .045       0   954.9     .07       0
Bank Sta=925,954.9
XS Rating Curve= 0 ,0
Exp/Cntr=0.3,0.1

Type RM Length L Ch R = 1 ,8550.8  ,1067.7,1072.8,1077.9
XS GIS Cut Line= 2
     1865286.982      399007.211     1866557.149      400269.064
#Sta/Elev= 30
       0 1584.75    69.6  1553.3   159.2  1527.2   218.8 1504.63   238.7 1501.09
   268.6 1492.04   298.4 1481.67   318.3 1472.65   477.4 1416.86   606.8  1378.2
     746  1361.7   845.5 1356.12   875.3 1347.65   905.2 1345.18     925 1340.03
   944.9 1339.17   974.8 1339.14   984.7 1339.15  1004.6 1346.96  1074.2 1355.11
    1124 1371.87  1163.8    1381  1372.6 1410.86  1452.2 1432.57  1511.9 1435.64
  1531.8 1438.59  1551.7 1444.13  1601.4 1453.49  1661.1 1468.43  1790.4 1493.12
#Mann= 3 , 0 , 0
       0     .07       0   944.9    .045       0   974.8     .07       0
Bank Sta=944.9,974.8
XS Rating Curve= 0 ,0
Exp/Cntr=0.3,0.1

Type RM Length L Ch R = 1 ,7478    ,1154,1154.2,1154.3
XS GIS Cut Line= 2
     1864662.951      399468.867     1865379.097      400625.117
#Sta/Elev= 30
       0  1615.5    49.6  1584.3    89.4    1545    99.3 1536.88   109.2 1532.23
     139 1505.87   188.6 1475.44   208.5 1469.99   248.2 1444.71   327.6  1398.2
   347.5 1389.79   367.3 1386.53   426.9 1361.14   446.7 1355.91   466.6  1353.9
   486.4 1342.09   506.3 1338.43   526.2 1327.34   536.1 1323.86   565.9 1323.94
   595.6 1324.31   625.4 1339.83     685 1351.55   724.7 1352.38     824 1360.84
     953 1377.36  1022.5 1388.73    1092 1407.36    1231 1455.05  1360.1 1506.96
#Mann= 3 , 0 , 0
       0      .1       0   565.9    .045       0   595.6      .1       0
Bank Sta=565.9,595.6
XS Rating Curve= 0 ,0
Exp/Cntr=0.3,0.1

Type RM Length L Ch R = 1 ,6323.9  ,951.2,946.9,942.5
XS GIS Cut Line= 2
     1863657.742      399937.617     1864373.888      401093.867
#Sta/Elev= 30
       0 1543.47    69.5 1522.46    89.4 1514.03   129.1 1503.56   228.3  1463.1
   297.8 1443.58   387.2 1409.82     407  1405.1   466.6 1382.24   526.2 1362.07
   625.4 1337.08   645.3 1333.24   655.2 1333.38   675.1 1324.97   704.8 1318.95
   724.7 1317.78   764.4 1308.72     814  1301.9   833.9 1301.82   836.6 1301.93
   913.3    1314   933.2 1326.06     963  1327.5   992.8 1341.11  1062.2 1362.43
  1082.1 1369.98    1102 1373.01  1141.7 1392.16  1240.9 1430.22  1360.1 1487.31
#Mann= 3 , 0 , 0
       0      .1       0     814    .045       0   836.6      .1       0
Bank Sta=814,836.6
XS Rating Curve= 0 ,0
Exp/Cntr=0.3,0.1

Type RM Length L Ch R = 1 ,5377    ,574.5,574.9,575.2
XS GIS Cut Line= 2
     1862857.902      400673.453     1863919.027      401816.957
#Sta/Elev= 30
       0 1571.31     100 1513.07     140 1502.67     190 1485.82     300 1433.24
     330 1423.46     370  1407.1     430 1374.92     450 1371.36     520 1339.42
     570 1321.11     640  1304.6     660 1303.58     680 1293.38     700 1286.87
  708.581286.381     740 1286.21   741.5 1286.23     760 1287.86     860  1309.2
     880  1316.2     910 1318.52     940 1317.86     970 1332.62    1110 1370.14
    1130 1373.78    1170 1386.84    1310 1447.12    1480 1496.84    1560    1515
#Mann= 3 , 0 , 0
       0      .1       0  708.58    .045       0   741.5      .1       0
Bank Sta=708.58,741.5
XS Rating Curve= 0 ,0
Exp/Cntr=0.3,0.1

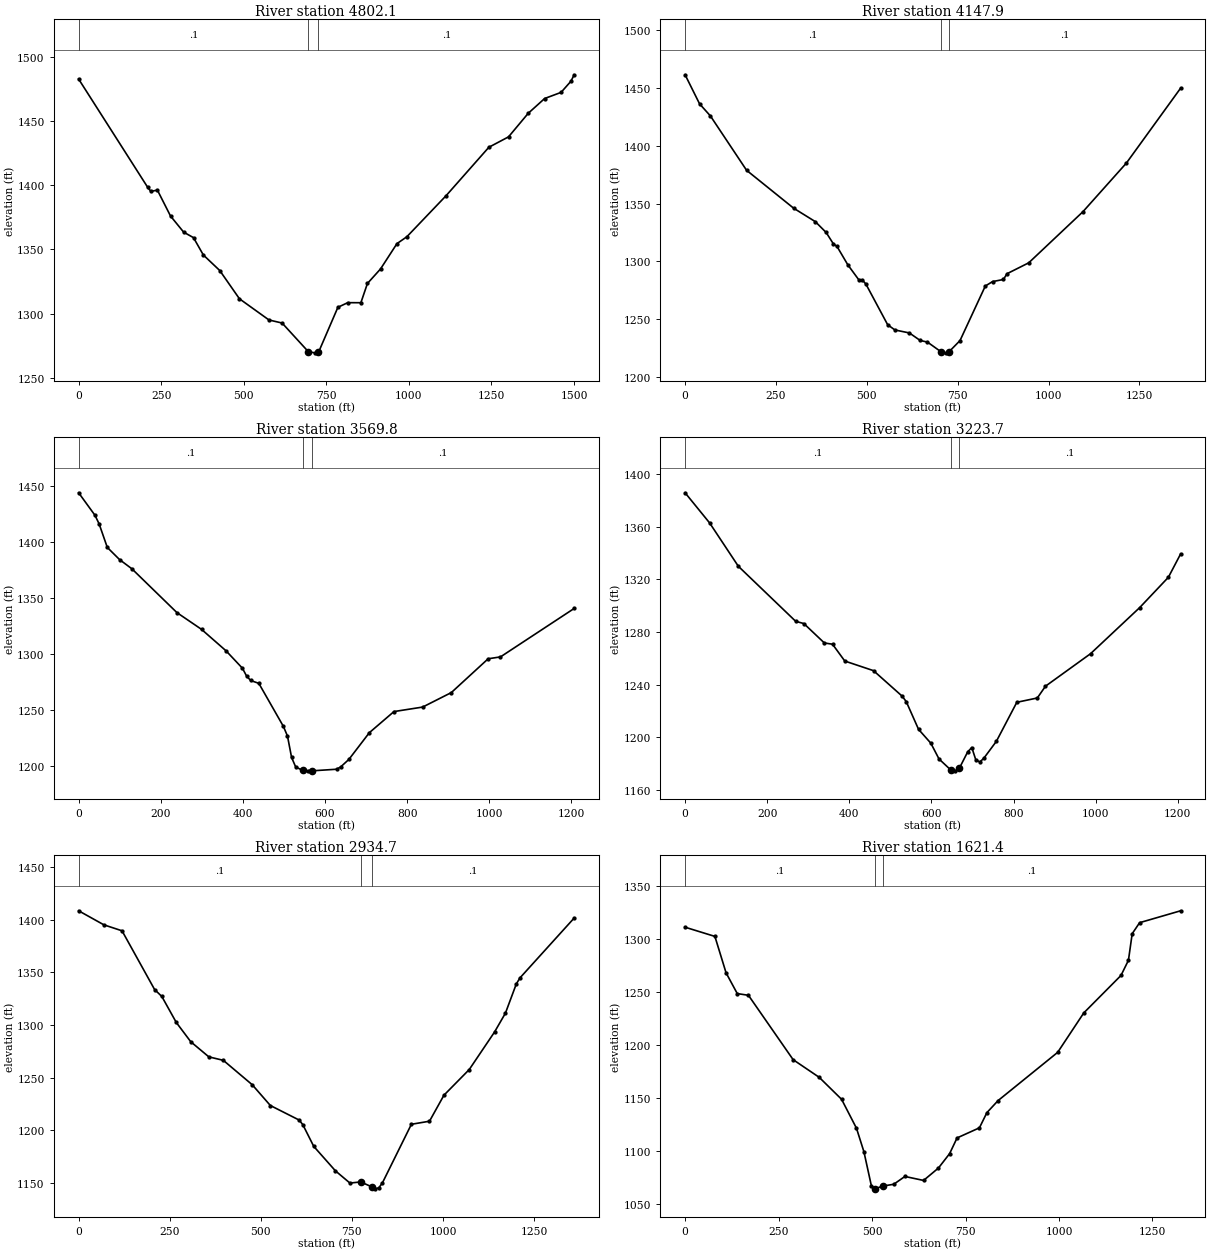
Type RM Length L Ch R = 1 ,4802.1  ,654.8,654.3,653.6
XS GIS Cut Line= 2
     1862573.179      401159.564     1863593.506      402259.666
#Sta/Elev= 30
       0 1482.52   208.7 1398.45   218.6 1395.12   238.5 1396.12   278.2 1375.98
     318 1363.42   347.8 1359.14   377.6 1345.66   427.3 1333.57   486.9 1311.58
   576.3  1295.1   616.1 1292.71   695.6  1270.4   715.4 1269.53  726.241269.909
     785 1304.96   814.8 1308.56   854.6 1308.52   874.4 1323.49   914.2 1334.83
   963.8 1354.49   993.7 1359.82  1112.9 1391.87  1242.1 1429.46  1301.7 1437.56
  1361.3 1455.89    1411 1467.39  1460.7 1472.15  1490.5 1480.79  1500.4 1485.85
#Mann= 3 , 0 , 0
       0      .1       0   695.6    .045       0  726.24      .1       0
Bank Sta=695.6,726.24
XS Rating Curve= 0 ,0
Exp/Cntr=0.3,0.1

Type RM Length L Ch R = 1 ,4147.9  ,578.1,578.1,578.1
XS GIS Cut Line= 2
     1862251.782      401674.104     1863178.865      402674.104
#Sta/Elev= 30
       0 1461.09    39.8 1436.02    69.7 1425.55   169.2 1378.68   298.6 1345.99
   358.3 1334.38   388.2 1325.01   408.1 1315.15     418 1312.97   447.9 1297.05
   477.8 1284.26   487.7 1284.13   497.7  1280.4   557.4 1245.43   577.3 1240.91
   617.1 1238.34     647 1231.82   666.9 1230.45  704.421222.027   716.6 1221.17
   726.4 1222.13   756.5 1231.75   826.1 1278.81     846 1282.65   875.9 1284.46
   885.9 1289.45   945.6 1298.84  1094.9 1342.99  1214.3  1384.9  1363.6 1449.57
#Mann= 3 , 0 , 0
       0      .1       0  704.42    .045       0   726.4      .1       0
Bank Sta=704.42,726.4
XS Rating Curve= 0 ,0
Exp/Cntr=0.3,0.1

Type RM Length L Ch R = 1 ,3569.8  ,345.6,346.1,346.2
XS GIS Cut Line= 2
     1861861.157      402062.125     1862681.469      402947.542
#Sta/Elev= 30
       0 1443.65    39.9 1423.53    49.9 1415.91    69.8 1394.94    99.8 1384.03
   129.7 1375.87   239.4  1336.8   299.3 1321.87   359.1 1302.71     399 1287.18
     409 1280.28     419 1276.26   438.9 1273.72   498.8 1235.29   508.7  1226.7
   518.7 1207.62   528.7 1199.16     546 1196.02   558.6  1195.7   568.6 1195.71
   628.4 1197.13   638.4 1199.24   658.4 1205.95   708.2 1229.76   768.1 1248.56
   837.9 1252.56   907.8 1265.49   997.5 1295.63  1027.5  1297.3    1207  1340.5
#Mann= 3 , 0 , 0
       0      .1       0     546    .045       0   568.6      .1       0
Bank Sta=546,568.6
XS Rating Curve= 0 ,0
Exp/Cntr=0.3,0.1

Type RM Length L Ch R = 1 ,3223.7  ,285,289,293.4
XS GIS Cut Line= 2
     1861613.761      402281.309     1862434.073      403166.726
#Sta/Elev= 30
       0 1385.82    59.8 1362.88   129.7 1329.98   269.3 1288.19   289.3 1286.45
   339.2 1271.71   359.1 1270.77     389 1257.98   458.9 1250.68   528.7  1231.3
   538.7 1227.14   568.6 1206.11   598.5 1195.59   618.5 1183.57   647.9 1175.01
   658.4 1174.57   668.3 1176.72   688.3 1188.98   698.3 1192.29   708.2 1182.81
   718.2 1181.31   728.2 1184.38   758.1 1196.95     808 1226.65   857.9 1229.92
   877.8 1238.87   987.6 1263.57  1107.3  1298.6  1177.1 1321.61    1207 1339.38
#Mann= 3 , 0 , 0
       0      .1       0   647.9    .045       0   668.3      .1       0
Bank Sta=647.9,668.3
XS Rating Curve= 0 ,0
Exp/Cntr=0.3,0.1

Type RM Length L Ch R = 1 ,2934.7  ,1317.6,1313.3,1309
XS GIS Cut Line= 2
     1861457.222      402307.409     1862173.367      403463.659
#Sta/Elev= 30
       0 1408.33    69.5 1394.96   119.1 1389.33   208.5 1333.59   228.3 1327.02
     268 1302.36   307.8 1284.02   357.4 1269.68   397.1  1266.4   476.5 1243.23
   526.2 1223.52   605.6 1209.65   615.5 1205.22   645.3 1184.74   704.8 1161.52
   744.6 1149.92   774.3 1150.98   804.1  1146.4     814 1144.43     824 1145.43
   833.9 1150.17   913.3  1205.7     963 1208.61  1002.7 1233.31  1072.2 1257.69
  1141.7 1293.36  1171.4 1311.16  1201.2 1338.82  1211.2  1344.6  1360.1 1401.44
#Mann= 3 , 0 , 0
       0      .1       0   774.3    .045       0   804.1      .1       0
Bank Sta=774.3,804.1
XS Rating Curve= 0 ,0
Exp/Cntr=0.3,0.1

Type RM Length L Ch R = 1 ,1621.4  ,1164.8,1169.7,1174.5
XS GIS Cut Line= 2
     1860325.277      403027.895     1861202.013      404021.818
#Sta/Elev= 30
       0 1311.05    79.7 1302.38   109.6 1268.01   139.5 1248.47   169.4 1246.84
     289 1186.12   358.7 1169.49   418.5 1148.79   458.4 1121.47   478.3  1099.3
   498.2 1067.24  507.351064.577   508.2 1064.33   528.3 1066.94     558 1068.63
   587.9 1076.01   637.8 1072.25   677.6 1083.95   707.5 1097.53   727.4 1112.34
   787.2 1121.86   807.2 1136.18   837.1 1147.55   996.5 1193.04  1066.3 1230.22
  1165.9 1265.58  1185.8 1279.88  1195.8 1304.92  1215.7 1315.33  1325.4 1326.55
#Mann= 3 , 0 , 0
       0      .1       0  507.35    .045       0   528.3      .1       0
Bank Sta=507.35,528.3
XS Rating Curve= 0 ,0
Exp/Cntr=0.3,0.1

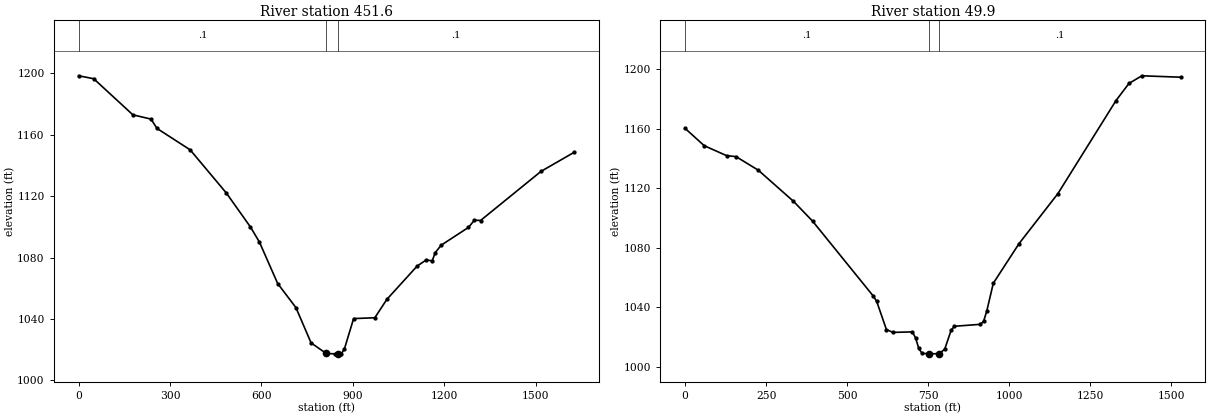
Type RM Length L Ch R = 1 ,451.6   ,389.9,401.7,413.6
XS GIS Cut Line= 4
     1859661.215      403344.735      1859743.68      403952.374
      1859895.59      404244.041     1860284.479      404806.541
#Sta/Elev= 30
       0 1198.38    49.4 1196.47     178 1172.95   237.4 1170.17   257.2 1164.08
     366 1150.13   484.6 1122.04   563.8 1099.88   593.4 1089.98   653.1 1063.07
   712.9 1047.42   762.7  1024.4   812.5 1017.52   840.3 1017.28   852.4  1017.3
   862.3 1017.38   872.3 1020.64   902.2 1040.24   971.8 1040.78  1011.4 1052.78
  1110.6 1074.43  1140.3 1078.41  1160.1 1077.85    1170 1083.19  1189.8 1088.08
    1279 1099.61  1298.8 1104.38  1318.7 1104.12  1516.9 1136.09  1625.9 1148.54
#Mann= 3 , 0 , 0
       0      .1       0   812.5    .045       0   852.4      .1       0
Bank Sta=812.5,852.4
XS Rating Curve= 0 ,0
Exp/Cntr=0.3,0.1

Type RM Length L Ch R = 1 ,49.9    ,51.3,49.9,48.5
XS GIS Cut Line= 4
     1859504.965      403461.923     1859465.902      403991.436
     1859448.541      404390.742     1859387.777       404985.36
#Sta/Elev= 30
       0 1160.27      59 1148.63   127.8 1141.97   157.3 1141.28   226.2  1132.1
   334.3 1111.26   393.3 1097.91   580.9 1047.44   590.9    1044   620.9 1025.07
   640.9 1023.16   700.8 1023.49   710.8 1019.47   720.8 1012.33   730.8 1009.09
   750.8 1008.74   783.9 1008.88   800.7 1011.85   820.7 1024.69   830.7 1027.27
   910.6 1028.57   920.6 1030.56   930.6 1037.63   950.6 1056.21  1030.2 1082.89
  1149.8 1116.42  1329.1 1178.99    1369 1190.48  1408.8 1195.63  1528.4 1194.66
#Mann= 3 , 0 , 0
       0      .1       0   750.8    .045       0   783.9      .1       0
Bank Sta=750.8,783.9
XS Rating Curve= 0 ,0
Exp/Cntr=0.3,0.1

Chan Stop Cuts=-1
Use User Specified Reach Order=0
Composite Channel Slope=5